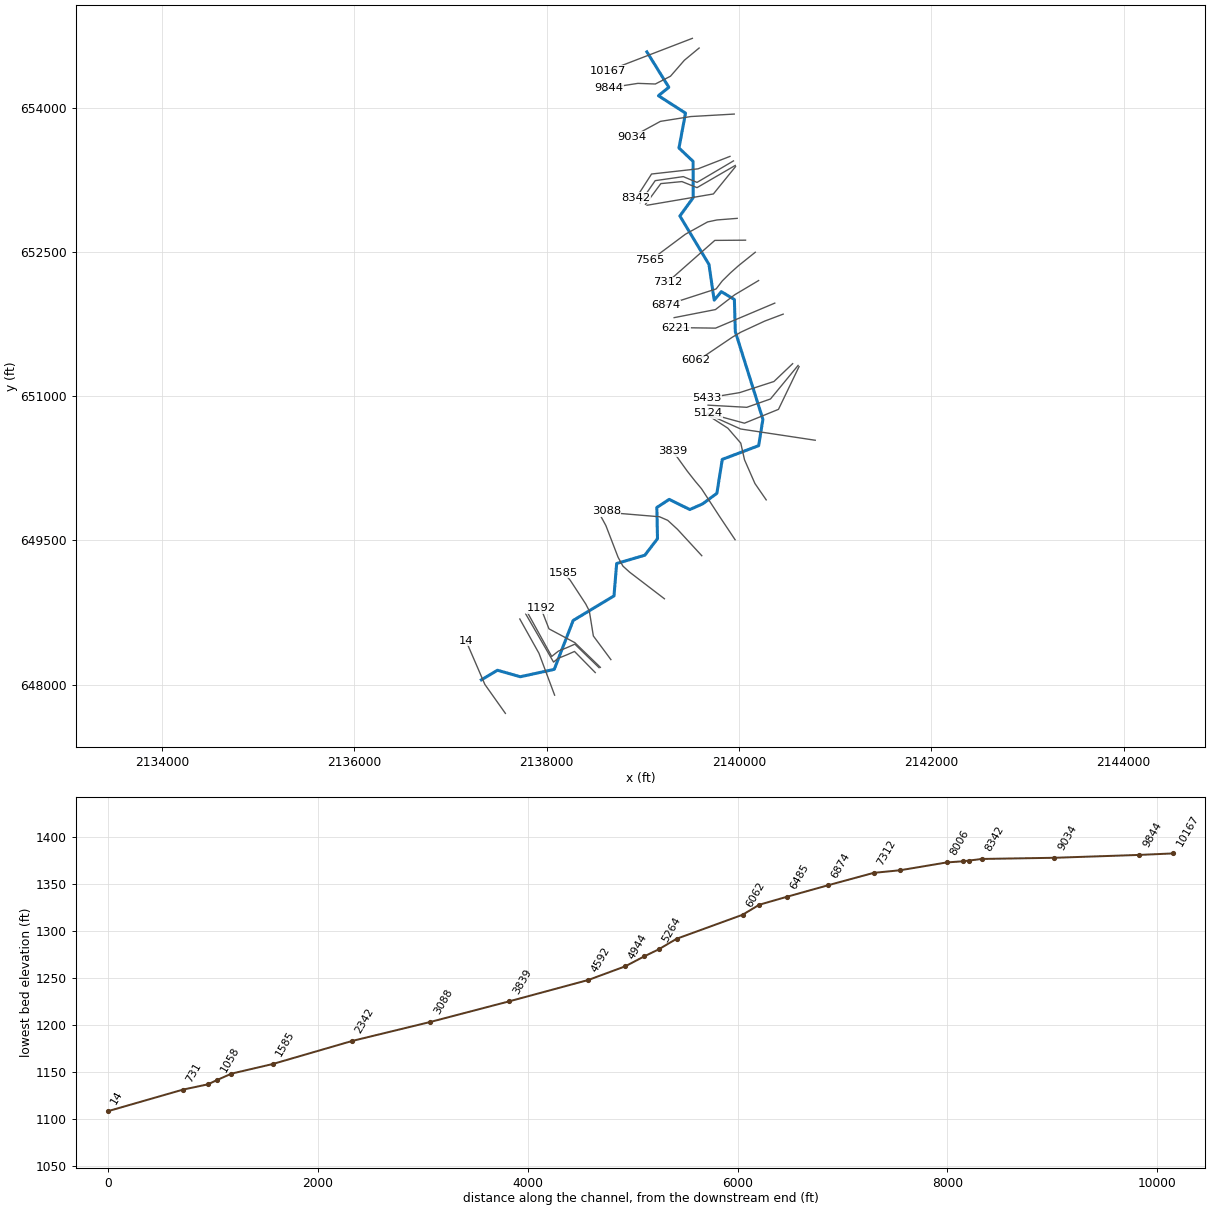
--- CHERRYFK.prj (project) ---

Proj Title=CHERRYFK
Current Plan=p01
Default Exp/Contr=0,0
English Units
Geom File=g01
Flow File=f01
Plan File=p01
BEGIN DESCRIPTION:
---------- MODELED AS PART OF WVEMD CTP PROGRAM, 2023----------
Stream Name: Cherry Fork
Flood Zone:  AFH
Upshur County, WV
HEC-RAS Version: RAS 6.3
Vertical Datum: NAVD88
Projection: NAD 1983 StatePlane West Virginia S FIPS 4702 (US Feet)
Terrain: 1-meter LIDAR (FEMA Region III 3DEP collected 2016-2018)
Land Use: 2019 NLCD
Hydrologic Method:
WV SIR2010-5033 regression equations
Additional Model Notes:
DS extent crosses county boundary into Lewis County
END DESCRIPTION:
DSS Export Rating Curves= 0
DSS Export Rating Curve Sorted= 0
DSS Export Volume Flow Curves= 0
DXF OffsetX= 0
DXF OffsetY= 0
DXF ScaleX= 0
DXF ScaleY= 0

--- CHERRYFK.p01 (plan) ---

Plan Title=Floodplain
Program Version=6.31
Short Identifier=Floodplain
Geom File=g01
Flow File=f01
Subcritical Flow
K Sum by GR= 0
Std Step Tol= 0.01
Critical Tol= 0.01
Num of Std Step Trials= 20
Max Error Tol= 0.3
Flow Tol Ratio= 0.001
Split Flow NTrial= 30
Split Flow Tol= 0.02
Split Flow Ratio= 0.02
Log Output Level= 0
Friction Slope Method= 1
Unsteady Friction Slope Method= 2
Unsteady Bridges Friction Slope Method= 1
Parabolic Critical Depth
Global Vel Dist= 0 , 0 , 0
Global Log Level= 0
CheckData=True
Encroach Param=-1 ,0,0, 0
Mapping Interval=1HOUR
Computation Time Step Use Courant=        0
Computation Time Step Use Time Series=    0
Computation Time Step Count To Double=0
Computation Time Step Max Doubling=0
Computation Time Step Max Halving=0
Computation Time Step Residence Courant=0
Run HTab= 0
Run UNet= 0
Run Sediment= 0
Run PostProcess= 0
Run WQNet= 0
Run RASMapper=-1
UNET Theta= 0
UNET Theta Warmup= 0
UNET ZTol= 0
UNET ZSATol= 0
UNET MxIter= 0
UNET Max Iter WO Improvement= 0
UNET MaxInSteps= 0
UNET DtIC= 0
UNET DtMin= 0
UNET MaxCRTS= 0
UNET WFStab= 0
UNET SFStab= 0
UNET WFX= 1
UNET SFX= 1
UNET Gravity=32.17405
UNET 1D Methodology=Finite Difference
UNET DSS MLevel= 1
UNET Pardiso=0
UNET DZMax Abort= 0
UNET Use Existing IB Tables= 0
UNET Froude Reduction=False
UNET Froude Limit= 0
UNET Froude Power= 0
UNET D1 Cores= 0
UNET WindReference=Eulerian
UNET WindDragFormulation=Hsu (1988)
UNET D2 Coriolis=0
UNET D2 Cores= 0
UNET D2 Theta= 1
UNET D2 Theta Warmup= 1
UNET D2 Z Tol= 0.01
UNET D2 Volume Tol= 0.01
UNET D2 Max Iterations= 20
UNET D2 Equation= 0
UNET D2 RampUpFraction=0.1
UNET D2 TimeSlices= 1
UNET D2 Turbulence Formulation=Non-Conservative (original)
UNET D2 Eddy Viscosity=0.3
UNET D2 Transverse Eddy Viscosity=0.1
UNET D2 Smagorinsky Mixing=0
UNET D2 BCVolumeCheck=0
UNET D2 Cores=0
UNET D2 SolverType=PARDISO (Direct)
UNET D2 Minimum Iterations= 3
UNET D2 Maximum Iterations= 30
UNET D2 Restart Number= 10
UNET D2 Relaxation Coeff=1.3
UNET D2 SOR Precondition Iterations= 10
UNET D2 ILUT Maximum Fill= 8
UNET D2 ILUT Tolerance=1E-08
UNET D2 Convergence Tolerance=0.00001
UNET D1D2 MaxIter= 0
UNET D1D2 ZTol=0.01
UNET D1D2 QTol=0.1
UNET D1D2 MinQTol=1
Write IC File= 0
Write IC File at Fixed DateTime=0
Write IC File at Sim End=0
Echo Input=False
Echo Parameters=False
Echo Output=False
Write Detailed= 0
HDF Write Warmup=0
HDF Write Time Slices=0
HDF Flush=0
HDF Compression= 1
HDF Chunk Size= 1
HDF Spatial Parts= 1
HDF Use Max Rows=0
HDF Fixed Rows= 1
Calibration Method= 0
Calibration Iterations= 20
Calibration Max Change=0.05
Calibration Tolerance=0.2
Calibration Maximum=1.5
Calibration Minimum=0.5
Calibration Optimization Method= 1
WQ AD Non Conservative
WQ ULTIMATE=-1
WQ Max Comp Step=1HOUR
WQ Output Interval=15MIN
WQ Output Selected Increments= 0
WQ Create Restart=0
WQ Fixed Restart=0
WQ System Summary=0
WQ Write To DSS=0
Sorting and Armoring Iterations= 10
XS Update Threshold= 0.02
Bed Roughness Predictor= 0
Hydraulics Update Threshold= 0.02
Energy Slope Method= 1
Volume Change Method= 1
Sediment Retention Method= 0
Sediment TS Multiplier= 1
Warm Up Method= 0
XS Weighting Method= 0
Number of US Weighted Cross Sections= 1
Number of DS Weighted Cross Sections= 1
Upstream XS Weight=0
Main XS Weight=1
Downstream XS Weight=0
Number of DS XS's Weighted with US Boundary= 1
Upstream Boundary Weight= 1
Weight of XSs Associated with US Boundary= 0
Number of US XS's Weighted with DS Boundary= 1
Downstream Boundary Weight= 0.5
Weight of XSs Associated with DS Boundary= 0.5
Percentile Method= 0
Sediment Output Level= 3
Mass or Volume Output= 0
Output Increment Type= 1
Profile and TS Output Increment= 1
Transport Output Increment 1
XS Output Flag= 0
XS Output Increment= 10
Read HDF5 Sediment Hotstart= 0
Sediment Hotstart Type= 0
Write Gradation File= 0
Read Gradation Hotstart= 0
Write HDF5 File= 1
Write Binary Output= 1
Write DSS Sediment File= 0
DSS Sediment Output Type= 1
SV Curve= 0
Specific Gage Flag= 0
Subcell Erosion Methods= 0
Subcell Deposition Methods= 0
Advection Scheme= 1
Matrix Solver= 0
Implicit Weighting Factor= 1
Maximum Outer Loop Convergence Iterations= 5
Convergence Maximum Absolute= 0.001
Convergence RMSE= 0.0001
Grain Fractions Max Abs Error= 0.001
Max Subgrid Regions= 1
Max Subgrid Length Scale= 3.402823E+38
Initial Layer Thickness= 3.402823E+38
Min Layer Thickness= 3.402823E+38
Max Layer Thickness= 3.402823E+38
Number of Layers= 5

--- CHERRYFK.f01 (steady flow) ---

Flow Title=Flows
Program Version=4.00
Number of Profiles= 1
Profile Names=01pct
River Rch & RM=CHERRYFK,Main,10167
     733
River Rch & RM=CHERRYFK,Main,4592
    1210
Boundary for River Rch & Prof#=CHERRYFK,Main      ,1
Up Type=0
Dn Type=3
Dn Slope=0.011122

--- CHERRYFK.g01 (geometry) ---

Geom Title=Geometry
Program Version=6.31

River Reach=CHERRYFK        ,Main
Reach XY= 30
     2139042.165      654584.557     2139270.094       654216.35
      2139162.01      654128.125     2139443.853      653946.955
      2139375.86      653584.185      2139522.29      653444.766
     2139523.807      653067.373     2139385.275       652876.53
     2139687.521      652372.453     2139742.093      652000.468
     2139816.381       652088.95     2139951.994       652007.25
     2139961.781      651672.438      2140248.66      650759.433
     2140204.419      650485.946     2139825.967      650342.835
     2139769.879      649989.652     2139621.189      649879.679
     2139488.494      649821.044     2139274.444       649926.81
      2139145.67      649842.649     2139152.395       649517.51
     2139020.559      649345.812      2138727.67      649259.133
     2138699.913      648922.489      2138275.16      648666.058
     2138078.794      648157.745     2137725.067      648080.824
     2137487.923       648148.332137320.84878696648048.969155903

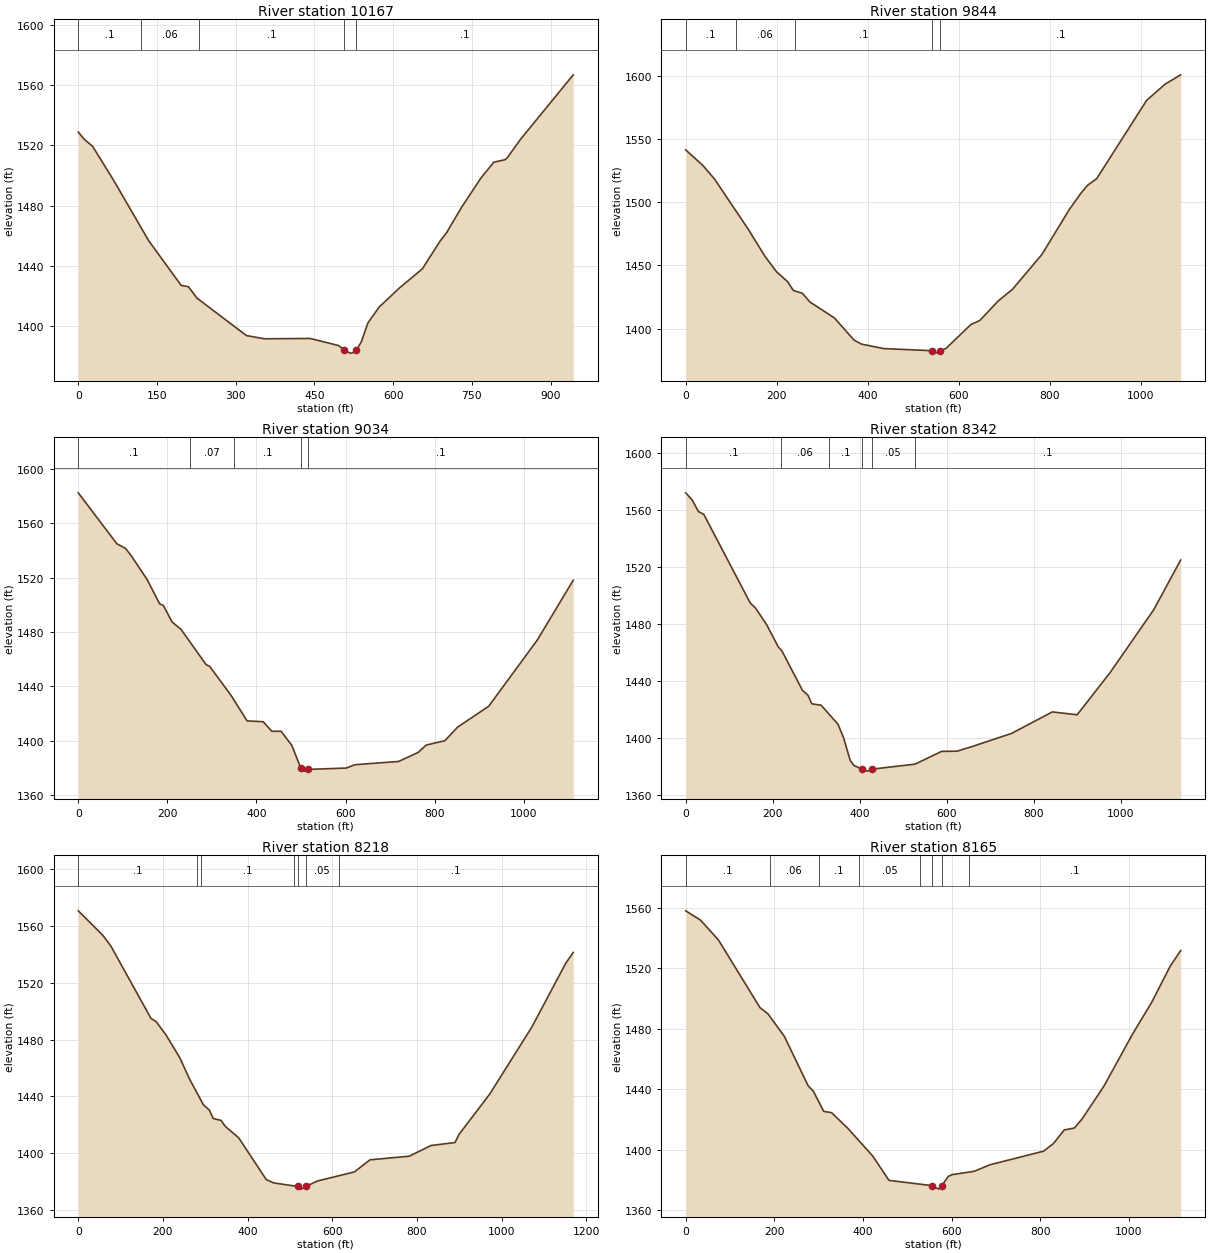
Type RM Length L Ch R = 1 ,10167   ,323.5,323.5,323.5
XS GIS Cut Line= 2
2139515.14326036654725.4513919742138635.18447966654386.527338629
#Sta/Elev= 30
       0 1528.82    11.8 1523.89    27.3 1519.35    67.5 1496.75   134.3 1456.73
   196.1 1427.18   209.8 1426.36   226.1  1418.8   320.4 1393.96   354.7 1391.84
   441.9 1392.05   496.1 1387.34  506.491384.414   517.6 1382.33   522.4 1382.43
  529.881384.415     539 1389.59   551.8 1402.35   573.3 1412.86   611.2 1425.31
   655.5 1438.15   689.5 1456.63   701.9 1462.21   729.7 1478.65   766.9 1498.23
   791.6 1508.81   813.3 1510.52   817.6 1511.92   843.3 1524.31     943 1566.74
#Mann= 5 ,-1,0
       0      .1       0     120     .06       0     230      .1       0
  506.49    .045       0  529.88      .1       0
Bank Sta=506.49,529.88
XS Rating Curve= 0 ,0
Exp/Cntr(USF)=0,0
Exp/Cntr=0.3,0.1

Type RM Length L Ch R = 1 ,9844    ,809.9,809.9,809.9
XS GIS Cut Line= 6
2139585.41923101654624.6829380842139431.91461676654497.279977679
2139287.34041906654330.9826050922139130.11338308 654250.13316226
2138948.84307633 654256.766023012138642.97196892654209.484293416
#Sta/Elev= 30
       0  1541.3    37.9 1528.97    63.8 1518.05   136.6 1479.08   173.8 1457.46
   199.6 1444.97   223.5 1437.39   236.7 1430.21   256.1  1428.1   273.1 1421.11
     327  1408.5   369.8 1391.08   386.5 1387.85   435.4 1384.32  542.271382.644
   549.3 1380.73   559.41382.642   572.1 1384.42   626.7 1403.28   646.7 1406.61
   686.8 1421.93   718.5 1431.23   782.9 1458.66   843.1 1494.13   868.3  1506.9
   883.4 1513.37   903.6  1518.7  1013.3 1580.53  1054.1 1593.35    1088 1600.65
#Mann= 5 ,-1,0
       0      .1       0  110.02     .06       0  239.49      .1       0
  542.27    .045       0   559.4      .1       0
Bank Sta=542.27,559.4
XS Rating Curve= 0 ,0
Exp/Cntr(USF)=0,0
Exp/Cntr=0.3,0.1

Type RM Length L Ch R = 1 ,9034    ,691.3,691.3,691.3
XS GIS Cut Line= 4
2139950.58223002653937.2348417872139499.40996591653911.513023567
2139183.00818386653861.3301407282138885.56794043653699.198568583
#Sta/Elev= 30
       0 1582.43    86.5 1544.98   106.6 1541.39   119.8  1535.7   154.7 1518.53
   182.7 1500.73   190.7 1499.67   210.7  1487.4   230.8  1481.9   286.9 1456.06
   294.9 1454.77     343 1433.39     379 1414.62   415.1 1414.03   434.4    1407
   455.2 1407.02   479.5 1396.55   499.7 1379.64   507.8 1377.68   515.9 1378.96
     601 1379.93   621.2  1382.4   718.9 1384.78     763 1391.45   780.9 1396.86
   822.7 1400.02   851.1 1409.96   921.3 1425.41  1030.6 1474.22    1111  1518.1
#Mann= 5 ,-1,0
       0      .1       0     250     .07       0     350      .1       0
   499.7    .045       0   515.9      .1       0
Bank Sta=499.7,515.9
XS Rating Curve= 0 ,0
Exp/Cntr(USF)=0,0
Exp/Cntr=0.3,0.1

Type RM Length L Ch R = 1 ,8342    ,124.9,124.9,124.9
XS GIS Cut Line= 4
 2139906.3400609653496.809751933 2139574.0243588653367.242618984
2139090.54700159653313.2563135882138930.98747675653064.919308768
#Sta/Elev= 30
       0 1571.76    15.2 1566.58    29.2 1558.61    41.5 1556.67   148.3 1494.48
   161.2 1490.62   186.2 1479.18   212.7 1463.72   221.3 1460.76   268.5 1433.12
   281.4 1429.54     290 1423.64   311.4 1422.73   350.1 1409.34   362.6 1400.21
   378.3 1383.89   386.7 1380.44  405.731377.782   418.9 1376.43   427.31377.782
   527.6 1381.33   588.3 1390.27   624.2 1390.44   660.4 1393.86     749 1402.85
   843.2 1417.99   900.3 1415.98   976.4 1445.75  1076.5 1489.77  1138.3 1524.58
#Mann= 6 ,-1,0
       0      .1       0     220     .06       0     330      .1       0
  405.73    .045       0   427.3     .05       0  526.68      .1       0
Bank Sta=405.73,427.3
XS Rating Curve= 0 ,0
Exp/Cntr(USF)=0,0
Exp/Cntr=0.3,0.1

Type RM Length L Ch R = 1 ,8218    ,53,53,53
XS GIS Cut Line= 5
2139942.70699201653449.8917499012139563.51627361653226.015310994
2139420.79504381 653286.182103952139128.35644548653244.205271655
 2138970.2437105653014.731921776
#Sta/Elev= 30
       0 1570.81    58.7 1553.34    77.3  1545.8   171.8 1494.98   184.1 1492.69
   207.3 1483.33   239.8  1467.3   263.1 1452.11   295.6 1434.16   309.5 1430.49
   318.8 1424.48   337.4 1423.11     347 1419.01   379.1 1410.82     444 1381.48
   461.3  1379.1   518.41376.568   526.5  1374.7  537.141376.568   565.5 1380.46
   652.4 1386.83   689.1 1395.34   781.7 1397.89   833.4 1405.44     890 1407.53
   899.2 1413.13   972.1 1441.69  1071.3 1488.78  1151.8 1533.95  1169.3 1541.51
#Mann= 7 ,-1,0
       0      .1       0     280     .06       0     290      .1       0
  510.35     .05       0   518.4    .045       0  537.14     .05       0
  615.23      .1       0
Bank Sta=518.4,537.14
XS Rating Curve= 0 ,0
Exp/Cntr(USF)=0,0
Exp/Cntr=0.3,0.1

Type RM Length L Ch R = 1 ,8165    ,158.1,158.1,158.1
XS GIS Cut Line= 5
2139960.89695267653402.3180066332139563.51627361 653171.44542901
2139406.80276637653234.410677453 2139187.1240107653213.422261305
2139027.61204798652997.941188857
#Sta/Elev= 30
       0 1558.15    33.2 1552.05    73.9 1538.84   167.4 1494.17   185.9 1489.86
   222.9 1474.94   276.4 1442.31   287.7 1438.94   311.5 1425.44   329.3 1424.55
   366.3 1414.07   421.8 1395.99   458.8 1379.76  556.841376.261     571 1373.97
  577.97 1376.26   592.5 1382.35   601.1 1383.54   651.2 1385.77     687 1390.11
   807.9 1399.09   830.1 1404.16   854.4 1413.14   877.2 1414.41   894.4  1420.3
     944 1442.13  1008.6 1476.58  1051.6 1497.48  1093.3 1521.37  1117.2 1531.87
#Mann= 8 ,-1,0
       0      .1       0     190     .06       0     300      .1       0
     390     .05       0  529.58     .06       0  556.84    .045       0
  577.97     .05       0  638.47      .1       0
Bank Sta=556.84,577.97
XS Rating Curve= 0 ,0
Exp/Cntr(USF)=0,0
Exp/Cntr=0.3,0.1

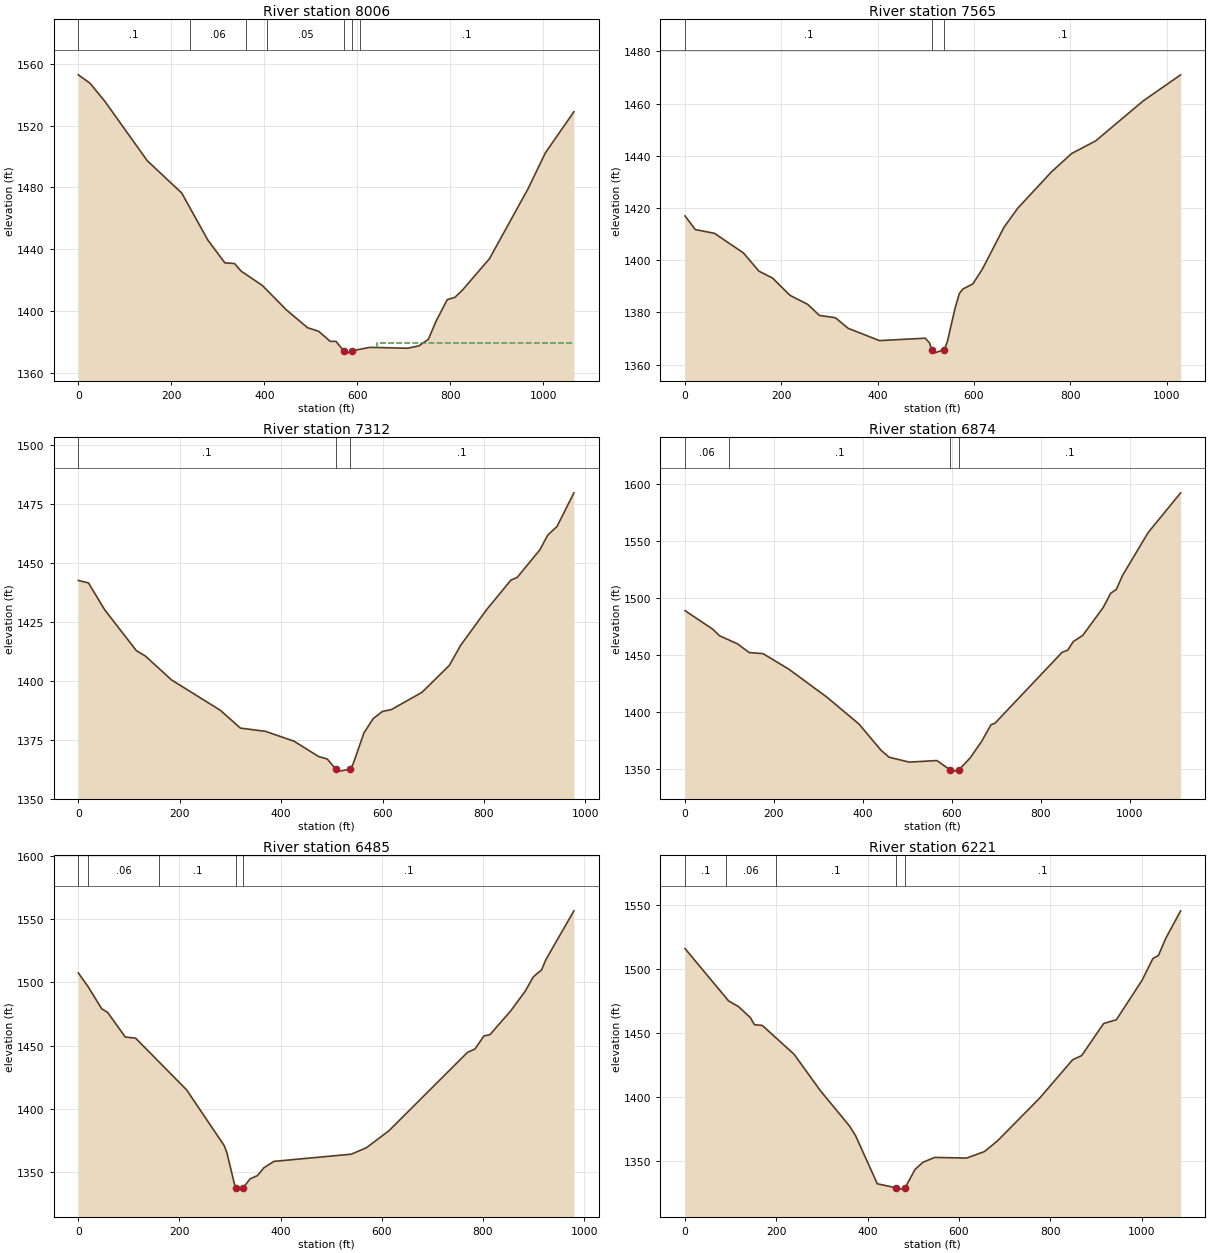
Type RM Length L Ch R = 1 ,8006    ,442,442,442
XS GIS Cut Line= 3
2139963.92545333653390.0368368172139733.58388364653105.708961733
2139043.75887025652988.138785538
#Sta/Elev= 30
       0 1552.87      25 1547.47    56.8 1535.82   148.3 1497.26   222.5 1476.33
   278.6 1445.88   315.1 1431.18     336 1430.71   350.2 1425.79   395.8 1416.51
   447.3 1400.75   493.1 1389.16   516.7  1386.9   541.8 1380.33     554 1380.35
  570.831374.166   578.4 1372.73  588.061374.165     627 1376.47   708.2  1375.9
   732.5 1377.45   752.8 1381.69   769.1 1393.29   793.4 1407.39   809.6 1408.81
   825.9 1413.48   884.2 1433.89   967.4  1479.3  1004.4  1502.4  1065.7 1528.97
#Mann= 7 ,-1,0
       0      .1       0     240     .06       0     360      .1       0
  405.92     .05       0  570.83    .045       0  588.06     .05       0
  605.92      .1       0
#XS Ineff= 2 , 0
                          641.85          1379.1
Permanent Ineff=
       F       F
Bank Sta=570.83,588.06
XS Rating Curve= 0 ,0
Exp/Cntr(USF)=0,0
Exp/Cntr=0.3,0.1

Type RM Length L Ch R = 1 ,7565    ,252.6,252.6,252.6
XS GIS Cut Line= 6
  2139981.292455652851.7445548332139770.64097342652835.136320338
2139672.81997484652814.3460075862139442.43624926652686.384649336
2139157.84823576652473.9713602512139074.88908409652419.871730924
#Sta/Elev= 30
       0 1416.99    21.2 1411.78    61.2 1410.32   121.4  1402.8   153.5 1395.82
   181.7 1393.19     218 1386.56   254.8 1383.11   279.1 1378.87   312.1    1378
   338.8 1373.93   403.7 1369.23   498.9 1370.15   507.7 1368.36  512.111365.803
   516.9 1364.43   538.7  1365.8     545 1369.02   560.1 1381.14   569.6 1387.26
   577.1    1389   597.8 1390.96   617.5 1396.63   662.5 1412.67     691 1419.96
   760.4 1433.76   802.8 1440.89   852.8 1445.74   951.3 1461.03  1029.2 1471.04
#Mann= 3 ,-1,0
       0      .1       0  512.11    .045       0   538.7      .1       0
Bank Sta=512.11,538.7
XS Rating Curve= 0 ,0
Exp/Cntr(USF)=0,0
Exp/Cntr=0.3,0.1

Type RM Length L Ch R = 1 ,7312    ,437.7,437.7,437.7
XS GIS Cut Line= 3
2140068.14604088652624.6442601712139748.53443979652622.377511227
2139255.51654448652187.161713992
#Sta/Elev= 30
       0  1442.5      20 1441.46      52 1430.07   114.6  1412.7     132  1410.5
     184  1400.3     280 1387.47   319.6  1379.9   368.9 1378.54   425.6 1374.33
   473.8 1367.85   490.8 1366.81  507.971362.502   514.8 1361.66  536.451362.502
   541.8 1364.64   563.2 1377.84   581.4  1383.9   599.5 1386.94   617.6 1387.78
   677.8 1395.09   731.6 1406.48   754.3 1415.11   805.6 1430.25   853.3 1442.69
   865.4 1443.77   910.2  1455.5   925.8 1461.75     944 1465.39   977.3 1479.65
#Mann= 3 ,-1,0
       0      .1       0  507.97    .045       0  536.45      .1       0
Bank Sta=507.97,536.45
XS Rating Curve= 0 ,0
Exp/Cntr(USF)=0,0
Exp/Cntr=0.3,0.1

Type RM Length L Ch R = 1 ,6874    ,388.9,388.9,388.9
XS GIS Cut Line= 6
2140169.28781392652499.0375830832139996.47713593652360.291141421
 2139909.7197635652283.0258760012139825.68548276652200.245201677
2139762.44381134652117.4015353322139234.60694051 651946.35922651
#Sta/Elev= 30
       0 1489.11    62.4 1472.85    77.6  1467.1   118.4 1459.92   144.3 1452.37
   175.4 1451.41   232.8 1437.98   318.5 1413.45   391.1 1389.76     441 1366.66
     459 1360.59   504.4 1356.29   566.6 1357.68   596.41349.508   604.4 1348.39
  616.121349.509   641.4 1359.98   667.5 1374.67   688.5  1389.2   696.9 1390.27
   848.3  1452.6   860.9 1454.48   873.5 1462.05   894.6 1467.37   940.8 1491.93
   957.6  1504.4   970.2 1507.75   984.3 1520.05  1041.7 1557.54  1114.9 1592.43
#Mann= 4 ,-1,0
       0     .06       0     100      .1       0   596.4    .045       0
  616.12      .1       0
Bank Sta=596.4,616.12
XS Rating Curve= 0 ,0
Exp/Cntr(USF)=0,0
Exp/Cntr=0.3,0.1

Type RM Length L Ch R = 1 ,6485    ,264.1,264.1,264.1
XS GIS Cut Line= 4
2140204.17777483652204.5437205362139955.11523655 652056.22557976
2139755.02566927651902.3105280122139325.46275212651818.356863421
#Sta/Elev= 30
       0 1507.61      20 1496.27    46.2 1479.18    57.9 1476.31    92.9 1456.76
   113.3 1455.86   214.2 1414.88   288.4 1370.78   293.6 1365.35   308.7 1340.36
  312.111337.483   314.6 1336.24  326.21 1337.48   339.8 1344.43   354.1 1346.93
     367 1353.15   386.7 1358.22   539.5 1363.91   569.6 1369.01   614.5  1382.6
   769.4 1444.55   784.4 1447.31     802 1457.57   814.2 1458.73     855 1477.46
   883.5 1492.97   899.8  1504.5   916.1 1509.97   924.4 1517.99     980 1556.77
#Mann= 5 ,-1,0
       0      .1       0      20     .06       0     160      .1       0
  312.11    .045       0  326.21      .1       0
Bank Sta=312.11,326.21
XS Rating Curve= 0 ,0
Exp/Cntr(USF)=0,0
Exp/Cntr=0.3,0.1

Type RM Length L Ch R = 1 ,6221    ,159.1,159.1,159.1
XS GIS Cut Line= 3
2140372.08510401651969.4734596842139756.42489702651709.217099454
2139339.45502955651714.814010427
#Sta/Elev= 30
       0 1516.06    95.4  1475.1   117.2 1470.61   143.2 1461.94   151.9 1456.49
   169.3 1455.89   238.8 1433.36   296.2 1404.92   360.3 1377.14   373.4 1369.66
   421.1 1331.93  461.861328.798   473.3 1327.75  481.951328.799   503.8 1343.21
     521 1348.79   547.1 1352.59   616.6 1352.07   655.7 1357.14   684.7 1365.68
   776.7 1399.03   848.7 1428.97   868.7  1432.3   916.7 1457.39   944.7 1460.37
  1000.7 1491.11  1024.7  1508.3  1036.7 1510.62  1052.7    1524  1085.4 1545.62
#Mann= 5 ,-1,0
       0      .1       0      90     .06       0     200      .1       0
  461.86    .045       0  481.95      .1       0
Bank Sta=461.86,481.95
XS Rating Curve= 0 ,0
Exp/Cntr(USF)=0,0
Exp/Cntr=0.3,0.1

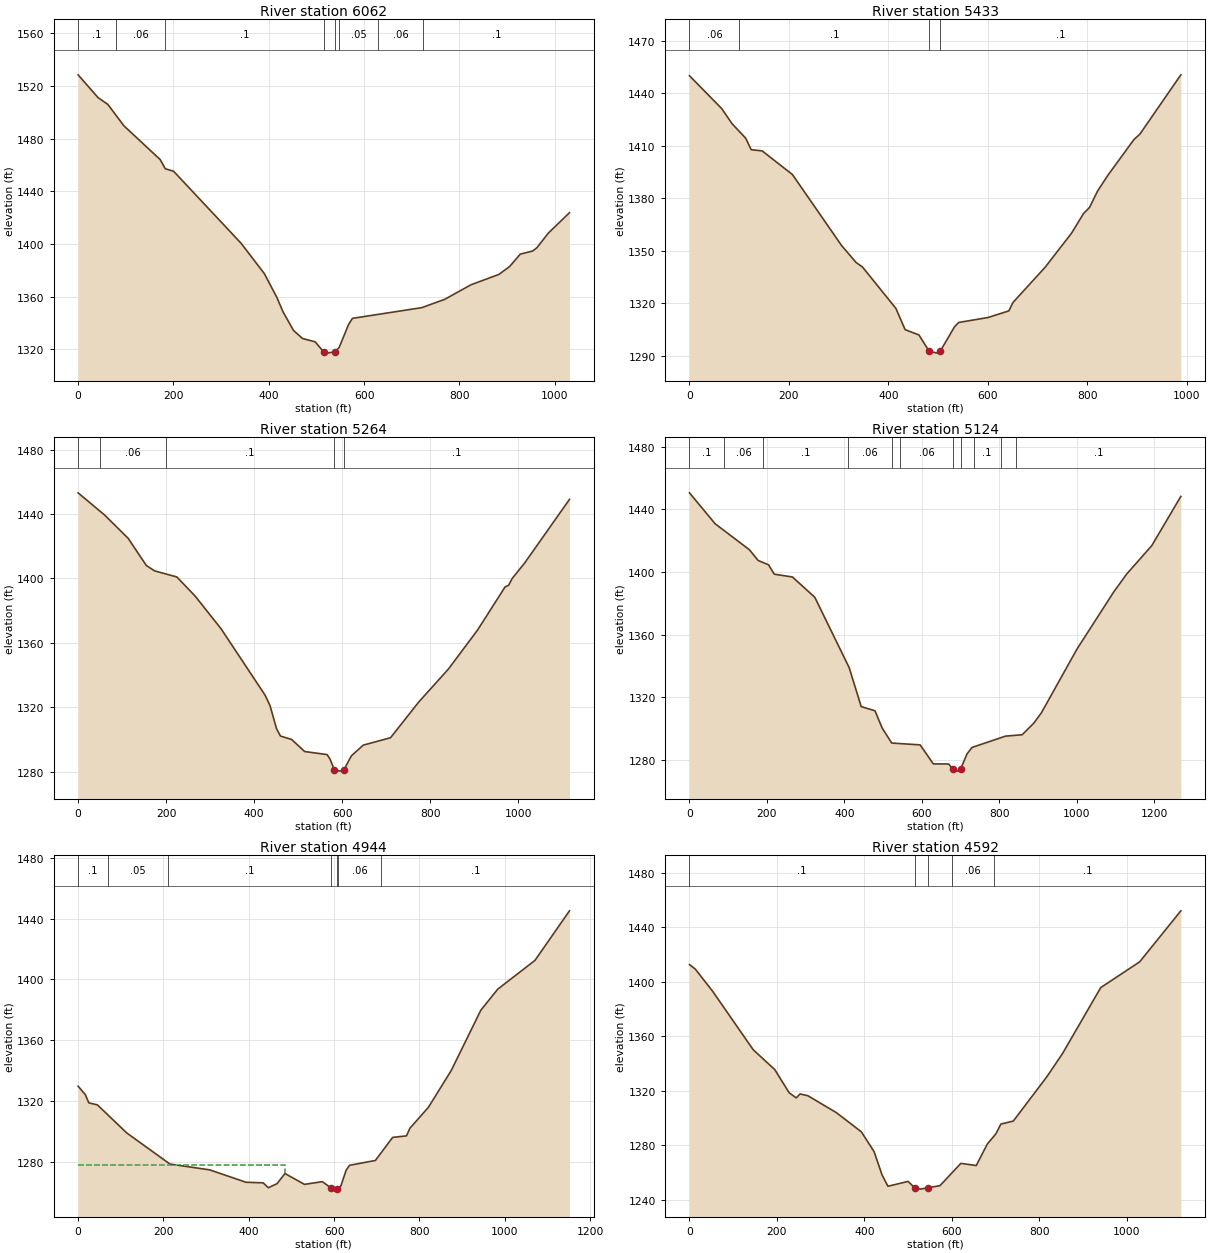
Type RM Length L Ch R = 1 ,6062    ,628.7,628.7,628.7
XS GIS Cut Line= 6
2140459.45980576 651854.886640432140268.63702467 651782.98258476
 2140020.1214456651667.5280912522139933.38835134651616.624321669
2139640.83316217651418.8773418372139552.44226284651374.508336082
#Sta/Elev= 30
       0 1528.54    41.9  1511.2    62.4 1506.07    96.1  1489.8   172.3 1464.11
   182.9 1457.16   200.3 1455.29   342.2 1400.44   390.8 1377.44     417 1359.38
   430.1 1348.32   451.9 1334.31   470.8 1328.21   497.4 1325.65   515.2 1317.99
   519.8 1317.09  538.311317.993   547.7 1321.44   567.5 1338.92   575.5 1343.51
   721.2 1351.66     769 1357.95     824 1368.99   882.9 1376.92   905.3 1382.91
   927.6  1392.3   953.5 1394.69   962.4 1397.13   986.3 1408.22  1030.8 1423.79
#Mann= 8 ,-1,0
       0      .1       0      80     .06       0  183.05      .1       0
   515.2    .045       0  538.31      .1       0  548.16     .05       0
  628.72     .06       0  723.72      .1       0
Bank Sta=515.2,538.31
XS Rating Curve= 0 ,0
Exp/Cntr(USF)=0,0
Exp/Cntr=0.3,0.1

Type RM Length L Ch R = 1 ,5433    ,169.8,169.8,169.8
XS GIS Cut Line= 4
2140557.98650197651339.205315051 2140363.4814808651153.687951171
2140006.78133849651037.9413967122139667.04222879650981.646657561
#Sta/Elev= 30
       0  1450.1      65 1431.27    85.4 1422.77   113.1 1414.37   124.1 1407.83
   146.2 1407.14     207 1393.64   305.9 1353.06   335.2 1343.34     348 1340.77
   415.2 1317.09   433.7 1304.99   461.5 1301.92  482.291292.529   499.4 1291.56
  504.021292.526     533 1306.61   541.4 1309.08   600.3 1311.91   642.3 1315.71
   650.5 1320.48   715.4 1340.69   768.5 1360.17   792.4 1371.31   804.6 1374.85
   820.6 1384.13   841.1 1393.06   893.9 1413.64   905.9 1416.74   988.2 1450.62
#Mann= 4 ,-1,0
       0     .06       0     100      .1       0  482.29    .045       0
  504.02      .1       0
Bank Sta=482.29,504.02
XS Rating Curve= 0 ,0
Exp/Cntr(USF)=0,0
Exp/Cntr=0.3,0.1

Type RM Length L Ch R = 1 ,5264    ,139.9,139.9,139.9
XS GIS Cut Line= 4
2140614.73170093651320.9534096462140327.49462138 650971.85941675
2140081.23053858650885.1072966742139678.25294855650907.494940565
#Sta/Elev= 30
       0 1453.11    60.7 1439.22   113.7 1424.89   155.1    1408     174 1404.66
   224.4 1400.89   265.9 1389.06   325.1 1368.66   425.1 1327.48   436.4 1320.88
     451 1306.71   459.8 1302.16   485.3 1300.03     515 1292.52   565.9 1290.65
   572.8 1287.76  582.111281.297   595.5 1280.37  604.421281.297     621 1289.84
   648.1  1296.5   710.1  1301.1   774.3 1323.29   841.5 1343.67   907.8 1367.89
   970.6 1394.76   978.6 1395.73   986.6 1399.96  1014.7 1409.45  1116.8 1449.04
#Mann= 5 ,-1,0
       0      .1       0      50     .06       0     200      .1       0
  582.11    .045       0  604.42      .1       0
Bank Sta=582.11,604.42
XS Rating Curve= 0 ,0
Exp/Cntr(USF)=0,0
Exp/Cntr=0.3,0.1

Type RM Length L Ch R = 1 ,5124    ,179.5,179.5,179.5
XS GIS Cut Line= 4
 2140624.7619523651308.8664363842140410.68010759650863.912014057
2140056.67548857 650719.791556512139677.48477017650823.334409505
#Sta/Elev= 30
       0 1450.55    66.2 1430.81     155 1414.14   177.2 1407.36   204.3 1404.54
     219 1398.57     266 1396.78   323.7  1383.8   412.5 1338.85   443.5 1313.99
   479.1 1311.33   497.8 1300.24   522.4  1290.7   595.8 1289.53   629.8 1277.38
   669.2 1277.32  680.941273.883   690.8 1272.76  700.071273.885   716.7 1283.71
   729.7 1287.88   816.1 1295.11   859.3    1296     889 1303.33     909 1310.04
  1000.9 1350.76  1095.8 1387.25  1129.4 1398.72  1194.2 1416.87  1269.1 1448.28
#Mann= 11 ,-1,0
       0      .1       0      90     .06       0     190      .1       0
     410     .06       0  523.78     .07       0  543.78     .06       0
  680.94    .045       0  700.07     .06       0  733.78      .1       0
  803.78     .06       0  843.78      .1       0
Bank Sta=680.94,700.07
XS Rating Curve= 0 ,0
Exp/Cntr(USF)=0,0
Exp/Cntr=0.3,0.1

Type RM Length L Ch R = 1 ,4944    ,352.2,352.2,352.2
XS GIS Cut Line= 3
2140793.01385353650542.1966707352140017.21065007650659.500247891
2139682.62885613650810.128704921
#Sta/Elev= 30
       0 1329.88      17 1324.31    25.1 1318.95    45.3 1317.61   114.1 1299.16
   215.3 1278.74   308.3 1274.94   393.4  1266.8   433.7  1266.4   445.8  1263.2
   466.1 1265.86   484.8 1272.53   530.5 1265.41   572.6 1267.19   593.2 1262.91
   599.6 1262.28   607.7 1262.65   615.8 1264.38   627.9 1274.57     636 1277.92
   696.7 1281.12   737.1 1296.26   769.5 1297.26   777.6  1302.3   820.9    1316
   874.4 1340.18   943.7 1379.75   983.3  1393.6  1070.6 1412.51  1151.5 1445.08
#Mann= 7 ,-1,0
       0      .1       0      70     .05       0     210      .1       0
   593.2    .045       0   607.7      .1       0     610     .06       0
     710      .1       0
#XS Ineff= 2 , 0
             486 1277.98
Permanent Ineff=
       F       F
Bank Sta=593.2,607.7
XS Rating Curve= 0 ,0
Exp/Cntr(USF)=0,0
Exp/Cntr=0.3,0.1

Type RM Length L Ch R = 1 ,4592    ,752.7,752.7,752.7
XS GIS Cut Line= 6
2140283.00674659649921.5883416682140165.46400267650092.512868583
2140057.35496692650339.0845539272140018.53549075650512.192475423
2139884.22998509650667.5576502532139664.24978201650809.728625759
#Sta/Elev= 30
       0 1412.49    13.1 1409.33    52.9 1392.96   145.6 1350.08     195 1335.46
   227.9 1318.45     244  1314.7   252.7 1317.59   270.8 1316.28   335.9 1303.86
   392.9 1289.81     422 1275.29   440.3 1258.13   453.7 1249.86   499.8 1253.41
  514.431248.835   528.1 1247.75  545.571248.835   572.6 1250.27   620.3 1266.64
   655.6 1265.07   680.7 1280.77   700.6 1288.37   711.9 1295.51   740.3 1297.69
   816.9 1330.19   852.5 1347.09   940.2 1395.64  1029.2 1414.56  1123.3 1451.98
#Mann= 5 ,-1,0
       0      .1       0  514.43    .045       0  545.57      .1       0
  599.16     .06       0  695.61      .1       0
Bank Sta=514.43,545.57
XS Rating Curve= 0 ,0
Exp/Cntr(USF)=0,0
Exp/Cntr=0.3,0.1

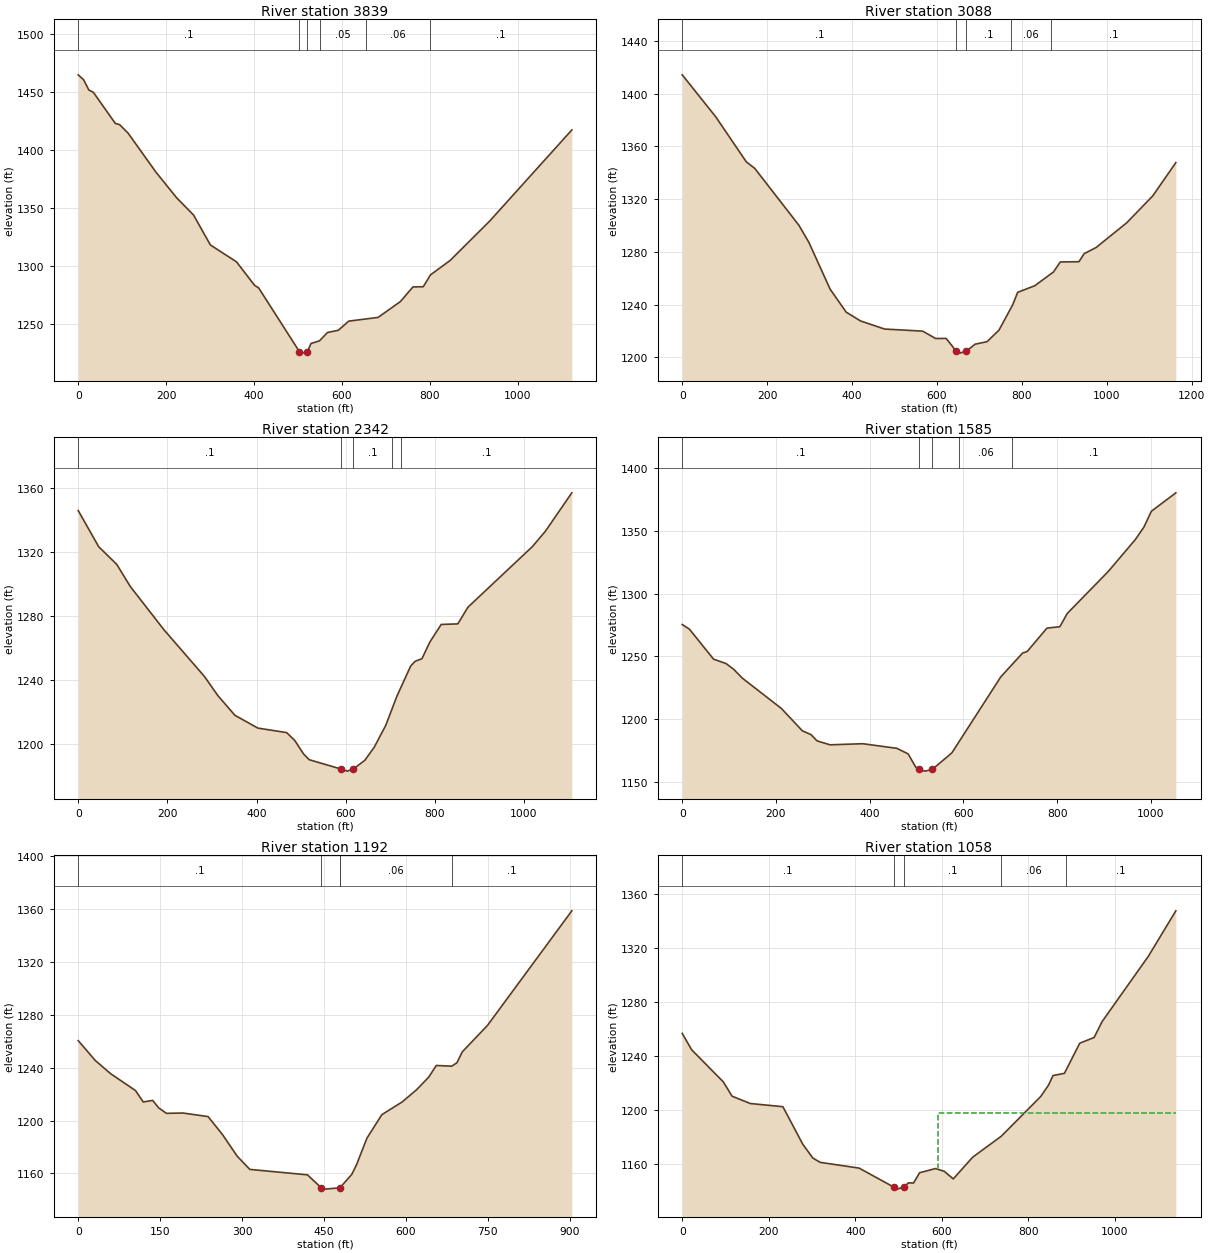
Type RM Length L Ch R = 1 ,3839    ,751.4,751.4,751.4
XS GIS Cut Line= 6
2139959.38469042649506.9835278392139797.07727225649750.240915343
2139610.54352459650037.1980185962139542.64995959650118.193919584
2139462.04382159650220.8639898452139314.95586118650425.329460174
#Sta/Elev= 30
       0 1465.11    12.3 1460.86    24.1 1452.08    34.5    1450    84.5 1423.16
    94.1 1422.18   113.4 1414.84   176.9 1381.14     224 1359.01   262.4 1344.17
   300.7 1318.36     360 1303.83     401 1283.64   410.6 1281.26  502.981226.466
   509.2 1225.08  521.311226.467   529.6 1233.42   548.7 1235.64     567 1242.87
   591.6 1244.78   615.5 1252.69     682 1255.86   732.9 1269.54   761.4 1282.18
   784.9 1282.34   801.2 1292.53   845.9 1304.98   935.4 1338.74  1122.8 1417.56
#Mann= 6 ,-1,0
       0      .1       0  502.98    .045       0  521.31      .1       0
  548.89     .05       0  654.69     .06       0  800.38      .1       0
Bank Sta=502.98,521.31
XS Rating Curve= 0 ,0
Exp/Cntr(USF)=0,0
Exp/Cntr=0.3,0.1

Type RM Length L Ch R = 1 ,3088    ,746.3,746.3,746.3
XS GIS Cut Line= 6
2139612.85257509649340.5655535912139360.03483926649615.471171752
2139259.03504126649708.4841090892139173.26355925649745.876094669
2138717.56565176649784.1834327582138619.15902442649806.461275339
#Sta/Elev= 30
       0 1414.22    79.1  1382.3     151  1348.2   170.9 1343.24   274.9 1300.08
   298.5 1287.01   348.2 1251.75     386 1234.28   419.9 1227.57   476.6 1221.42
   566.3 1219.83   596.9 1214.24   621.6 1214.31  645.48 1204.65   653.7 1203.15
  669.041204.648   689.9 1209.93   717.9 1211.83     746 1220.56   778.1 1239.64
   790.1 1249.27   830.3 1254.24   874.4  1264.7   890.5 1272.31   934.4 1272.48
   946.7 1278.59   974.8 1283.25  1047.1 1302.06  1108.3 1322.41  1162.6 1347.63
#Mann= 5 ,-1,0
       0      .1       0  645.48    .045       0  669.04      .1       0
  774.39     .06       0  869.03      .1       0
Bank Sta=645.48,669.04
XS Rating Curve= 0 ,0
Exp/Cntr(USF)=0,0
Exp/Cntr=0.3,0.1

Type RM Length L Ch R = 1 ,2342    ,757,757,757
XS GIS Cut Line= 6
2139224.34646234648892.3594290022138862.11752801649169.575410008
2138792.34174892649232.8538267612138742.57970934649324.241439253
2138615.60128875649654.2292963422138568.17717101 649741.48437117
#Sta/Elev= 30
       0 1345.86    45.9 1323.26    86.5 1312.18   116.9 1298.34   192.6 1271.22
   283.3 1242.07   313.4 1230.09   351.5 1217.83     403 1209.82   467.5 1207.01
   485.8 1202.08   505.4 1193.69   518.2 1190.06  589.581184.211   603.8 1182.91
  616.851184.211   642.7  1189.6     664 1197.83   689.9 1211.54   714.7 1229.63
   745.8 1248.63   755.6 1251.57   771.1 1253.22   788.7 1263.57   814.3 1274.64
   851.6 1274.99   874.3 1285.43  1018.6 1323.26  1047.8 1332.84  1107.3 1356.95
#Mann= 5 ,-1,0
       0      .1       0  589.58    .045       0  616.85      .1       0
   704.4     .06       0   724.4      .1       0
Bank Sta=589.58,616.85
XS Rating Curve= 0 ,0
Exp/Cntr(USF)=0,0
Exp/Cntr=0.3,0.1

Type RM Length L Ch R = 1 ,1585    ,392.7,392.7,392.7
XS GIS Cut Line= 6
2138667.73274617648259.1461285052138485.24689068648505.286384255
 2138443.2840481648765.5201157632138405.90715434648838.250285253
  2138244.736873649085.0306315872138175.44862576649164.559672013
#Sta/Elev= 30
       0 1275.37    15.3 1271.72    66.8 1247.76    93.5 1244.21   109.3 1239.83
     128 1232.67   211.6 1208.38   256.2 1190.59   274.8 1187.51   287.6 1182.54
   315.4 1179.37   385.1 1180.26   457.8  1176.6     482 1172.14   498.2 1161.58
  504.761159.689   518.4 1158.38  533.291159.689   575.3 1172.94   679.8 1233.64
   726.1 1252.56   736.2 1253.92   778.2 1272.51   805.7 1273.64   821.5 1284.19
   909.3 1317.84   966.9 1343.26   985.1 1353.13    1001 1365.78  1053.2 1380.49
#Mann= 5 ,-1,0
       0      .1       0  504.76    .045       0  533.29      .1       0
  591.17     .06       0  702.94      .1       0
Bank Sta=504.76,533.29
XS Rating Curve= 0 ,0
Exp/Cntr(USF)=0,0
Exp/Cntr=0.3,0.1

Type RM Length L Ch R = 1 ,1192    ,133.8,133.8,133.8
XS GIS Cut Line= 4
2138558.10367217648178.8012774922138292.49104963648435.776091176
2138023.63924875648579.3796635292137940.50033845648793.165432896
#Sta/Elev= 30
       0 1260.51    31.3 1245.46    59.6  1235.4   104.9 1222.74     119 1214.09
   136.3 1215.27   147.4 1209.61   161.5 1205.49   191.9 1205.72   237.8 1203.03
   264.3 1189.35   291.1 1173.09   314.2 1163.08   419.8 1158.97  445.091149.146
   451.6 1148.16  479.041149.146   500.9 1159.28   509.8  1166.8   528.7 1186.75
   555.9 1204.47   593.3 1214.15   619.4 1223.29     642 1232.98   655.6 1241.71
   683.9 1241.17   693.5 1243.77   703.2 1251.98   749.3 1271.96   903.8 1358.68
#Mann= 5 ,-1,0
       0      .1       0  445.09    .045       0  479.04      .1       0
  479.58     .06       0  684.38      .1       0
Bank Sta=445.09,479.04
XS Rating Curve= 0 ,0
Exp/Cntr(USF)=0,0
Exp/Cntr=0.3,0.1

Type RM Length L Ch R = 1 ,1058    ,90.9,90.9,90.9
XS GIS Cut Line= 6
2138544.89165461648175.094295842 2138292.9425095648419.903181787
2138216.43973264 648386.241959972138121.57628933648347.480553028
2138052.05199674648292.0381402632137803.86958998648742.550260638
#Sta/Elev= 30
       0 1256.89    21.8 1244.75    94.8 1221.01   115.1 1210.38   157.2 1204.94
   232.6 1202.57   278.5 1174.81   301.8 1164.53   318.7 1161.35   408.9 1157.06
  488.691143.022   495.7  1141.5  513.121143.023   522.3 1146.13   534.5 1146.04
   548.5 1153.64   585.5 1156.75   605.5 1154.69   626.3 1149.07   671.2 1165.17
   737.2 1180.69   828.5 1210.18   846.8 1218.77   856.7 1225.65   883.2  1227.3
   918.5  1249.6   951.8 1253.88   970.1 1265.56  1077.6 1314.28  1140.6 1347.72
#Mann= 5 ,-1,0
       0      .1       0  488.69    .045       0  513.12      .1       0
  736.28     .06       0  886.28      .1       0
#XS Ineff= 2 , 0
                           590.8         1198.28
Permanent Ineff=
       F       F
Bank Sta=488.69,513.12
XS Rating Curve= 0 ,0
Exp/Cntr(USF)=0,0
Exp/Cntr=0.3,0.1

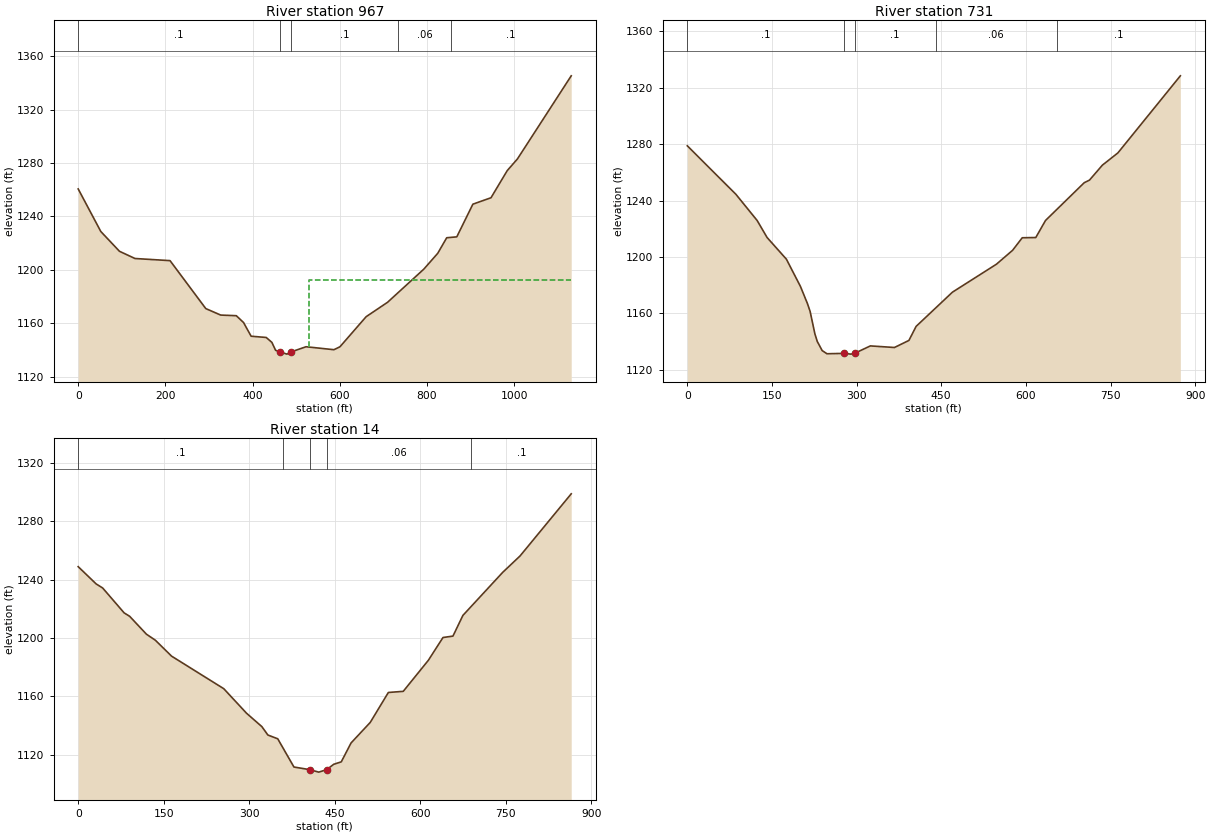
Type RM Length L Ch R = 1 ,967     ,236.7,236.7,236.7
XS GIS Cut Line= 6
2138505.12112808648124.1614299862138289.43996606648344.036077548
2138212.93718921 648310.37485573 2138118.0737459648271.613448789
2138071.39237258 648233.286575832137782.98995142648732.483263926
#Sta/Elev= 30
       0 1260.66    51.9 1228.73    94.7  1213.9   130.3 1208.49   210.7 1206.89
   292.7 1170.94   326.9 1166.08   362.7  1165.6   379.3 1160.49   396.7 1150.22
   431.3 1149.28   444.3 1145.61   452.9 1139.62   463.31138.468   478.8 1136.79
  488.521138.468   522.7 1142.32   586.7 1140.11   600.5 1142.31   660.6 1164.87
   709.5 1175.61   792.8 1200.49   824.8 1212.39   845.4 1224.06   868.5 1224.72
   905.4 1249.22     947 1254.06   984.2 1274.39  1007.6 1283.14    1131 1345.47
#Mann= 5 ,-1,0
       0      .1       0   463.3    .045       0  488.52      .1       0
  734.46     .06       0  854.46      .1       0
#XS Ineff= 2 , 0
                           529.4         1192.67
Permanent Ineff=
       F       F
Bank Sta=463.3,488.52
XS Rating Curve= 0 ,0
Exp/Cntr(USF)=0,0
Exp/Cntr=0.3,0.1

Type RM Length L Ch R = 1 ,731     ,716.4,716.4,716.4
XS GIS Cut Line= 3
2138082.32615136647889.3320815172137919.68616794648324.663731759
2137720.32577931648681.848045488
#Sta/Elev= 30
       0 1278.78    86.2 1244.39   123.7  1225.9   141.4 1213.81   175.6 1198.47
   200.5 1179.16   212.9    1167   217.6 1161.49   226.1 1145.53   230.4  1140.1
     239 1133.71   247.5 1131.46   278.2 1131.74   290.2  1131.2   296.91131.846
   324.4 1137.02   367.1  1135.9   392.7 1140.89   405.5 1150.86   469.9  1175.1
   547.8 1194.89   576.5 1204.76   593.6 1213.64   617.6 1213.81   634.8 1225.88
   703.5 1252.67   712.7 1254.46   735.6 1265.07   763.1 1273.76   873.8 1328.37
#Mann= 5 ,-1,0
       0      .1       0   278.2    .045       0   296.9      .1       0
     440     .06       0  654.72      .1       0
Bank Sta=278.2,296.9
XS Rating Curve= 0 ,0
Exp/Cntr(USF)=0,0
Exp/Cntr=0.3,0.1

Type RM Length L Ch R = 1 ,14      ,,,
XS GIS Cut Line= 3
2137570.37150833647699.5163751272137356.70943195 648001.04995378
2137160.39777958648455.659047536
#Sta/Elev= 30
       0 1248.88    31.5 1237.06    42.9 1234.29    80.5 1217.27    90.3 1214.88
   119.7 1202.64   135.3 1198.53   163.8 1187.62   255.3 1165.34   295.4 1148.48
   322.1 1139.38   332.7 1133.62     350 1131.04   378.4 1111.71  405.821109.941
     422 1108.22  435.95 1109.94   448.1 1113.58   461.4 1115.26   478.6  1128.2
   512.2 1142.24     544 1162.75   570.1 1163.52   614.2 1184.81   639.8 1200.37
   657.3 1201.35   674.7 1215.49   744.5 1244.97   774.9 1256.18   864.7 1298.74
#Mann= 5 ,-1,0
       0      .1       0     360     .06       0  405.82    .045       0
  435.95     .06       0  689.56      .1       0
Bank Sta=405.82,435.95
XS Rating Curve= 0 ,0
Exp/Cntr(USF)=0,0
Exp/Cntr=0.3,0.1
LCMann Table=0

Chan Stop Cuts=-1
Use User Specified Reach Order=0
Composite Channel Slope=5